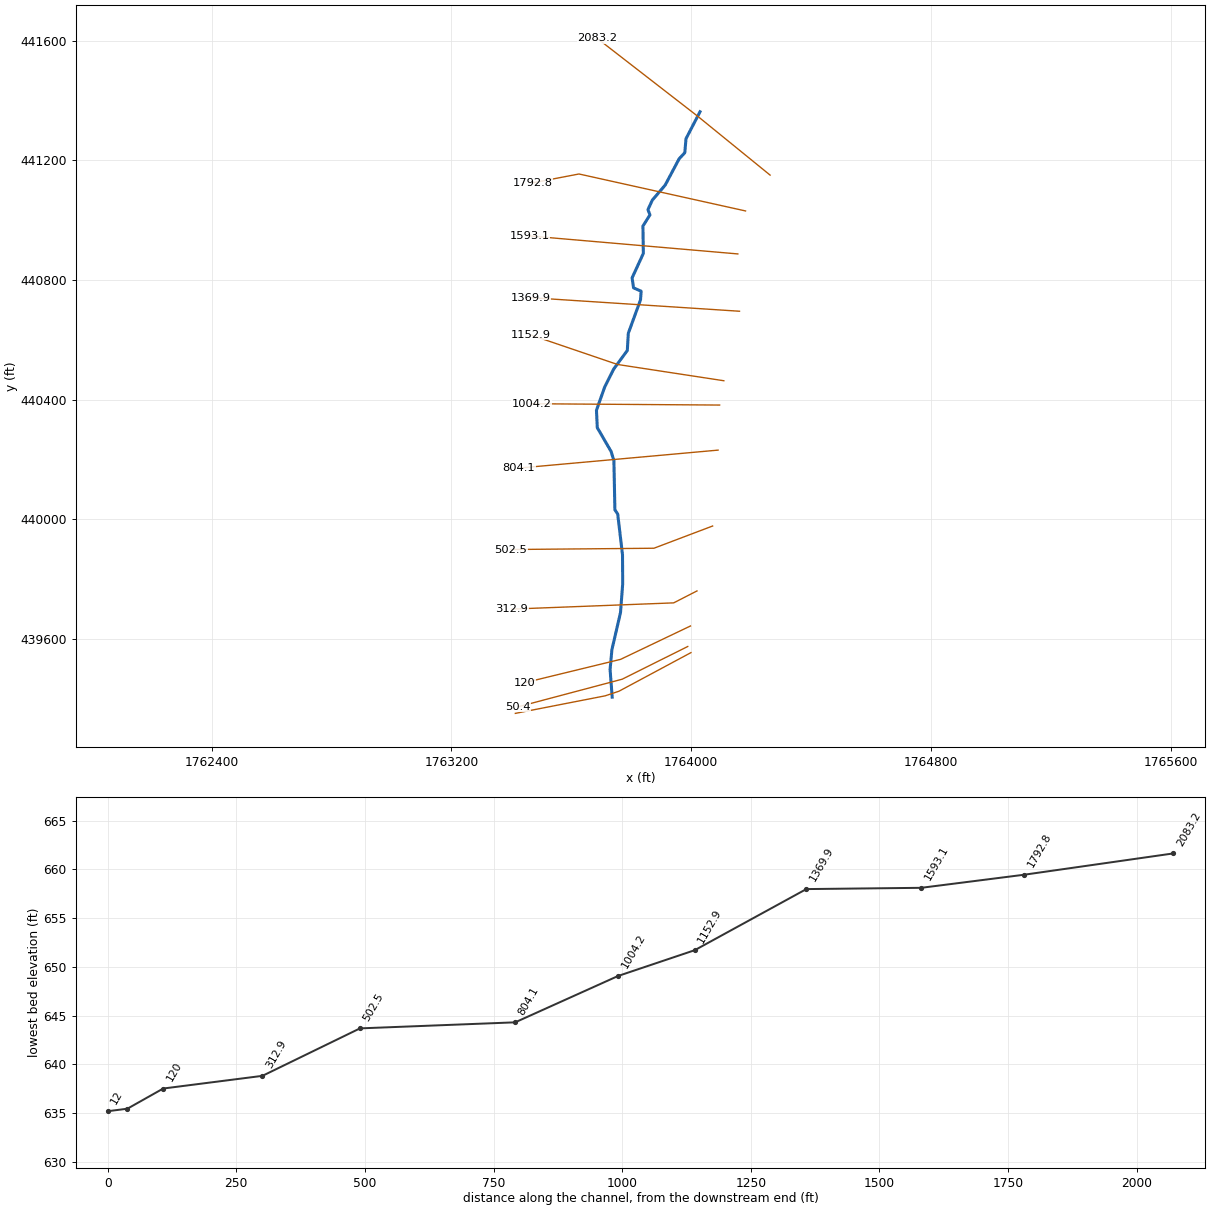
--- LFBULLCK.prj (project) ---

Proj Title=LFBULLCK
Current Plan=p01
Default Exp/Contr=0,0
English Units
Geom File=g01
Flow File=f01
Plan File=p01
BEGIN DESCRIPTION:
END DESCRIPTION:
DSS Export Rating Curves= 0
DSS Export Rating Curve Sorted= 0
DSS Export Volume Flow Curves= 0
DXF OffsetX= 0
DXF OffsetY= 0
DXF ScaleX= 0
DXF ScaleY= 0

--- LFBULLCK.p01 (plan) ---

Plan Title=Floodplain
Program Version=4.00
Geom File=g01
Flow File=f01
K Sum by GR=0
Std Step Tol=0.01
Critical Tol=0.01
Num of Std Step Trials=20
Max Error Tol=0.3
Flow Tol Ratio=0.001
Split Flow NTrial=30
Split Flow Tol=0.02
Split Flow Ratio=0.02
Log Output Level=0
Friction Slope Method=1
Unsteady Friction Slope Method=2
Unsteady Bridges Friction Slope Method=1
Global Log Level=0
CheckData=False
Run HTab=0
Run UNet=0
Run PostProcess=0
UNET Theta=0
UNET Theta Warmup=0
UNET ZTol=0
UNET ZSATol=0
UNET MxIter=0
UNET MaxInSteps=0
UNET DtIC=0
UNET DtMin=0
UNET MaxCRTS=0
UNET WFStab=0
UNET SFStab=0
UNET WFX=0
UNET SFX=0
UNET DSS MLevel=0
UNET DZMax Abort=0
UNET Convert EG Bridges=0
UNET Use Existing IB Tables=0
UNET Froude Limit=0
UNET Froude Power=0
Write IC File=0
Echo Input=False
Echo Output=False
Write Detailed=0

--- LFBULLCK.f01 (steady flow) ---

Flow Title=NFF Regression Equation
Program Version=4.00
Number of Profiles=1
Profile Names=P100yr
River Rch & RM=LFBULLCK,Main      ,2083.2
956.7676
River Rch & RM=LFBULLCK,Main      ,502.5
1041.832
River Rch & RM=LFBULLCK,Main      ,120
1043.820
Boundary for River Rch & Prof#=LFBULLCK,Main      ,1
Up Type=0
Dn Type=3
Dn Slope=0.014432

--- LFBULLCK.g01 (geometry) ---

Geom Title=USGS 10m DEM
Program Version=4.10

River Reach=LFBULLCK        ,Main
Reach XY= 30
     1764029.622      441362.191     1763982.845       441271.98
     1763978.836      441225.204     1763960.125      441205.156
     1763913.348      441116.949     1763870.581      441066.831
      1763855.88      441034.756     1763862.562      441017.382
     1763839.174      440979.961     1763840.511      440888.412
     1763803.089      440806.887     1763807.767      440773.475
      1763833.16      440762.116     1763831.156      440733.381
     1763790.393      440621.452     1763787.052      440563.983
     1763741.612      440501.838     1763711.541      440441.696
     1763684.143      440364.181     1763686.817      440306.044
     1763732.925       440226.39      1763742.28      440195.652
     1763745.621      440031.265     1763754.976      440017.233
     1763771.014      439881.247     1763771.682      439784.352
     1763764.332      439687.725     1763735.598      439563.433
     1763729.583      439497.278     1763736.599       439404.98

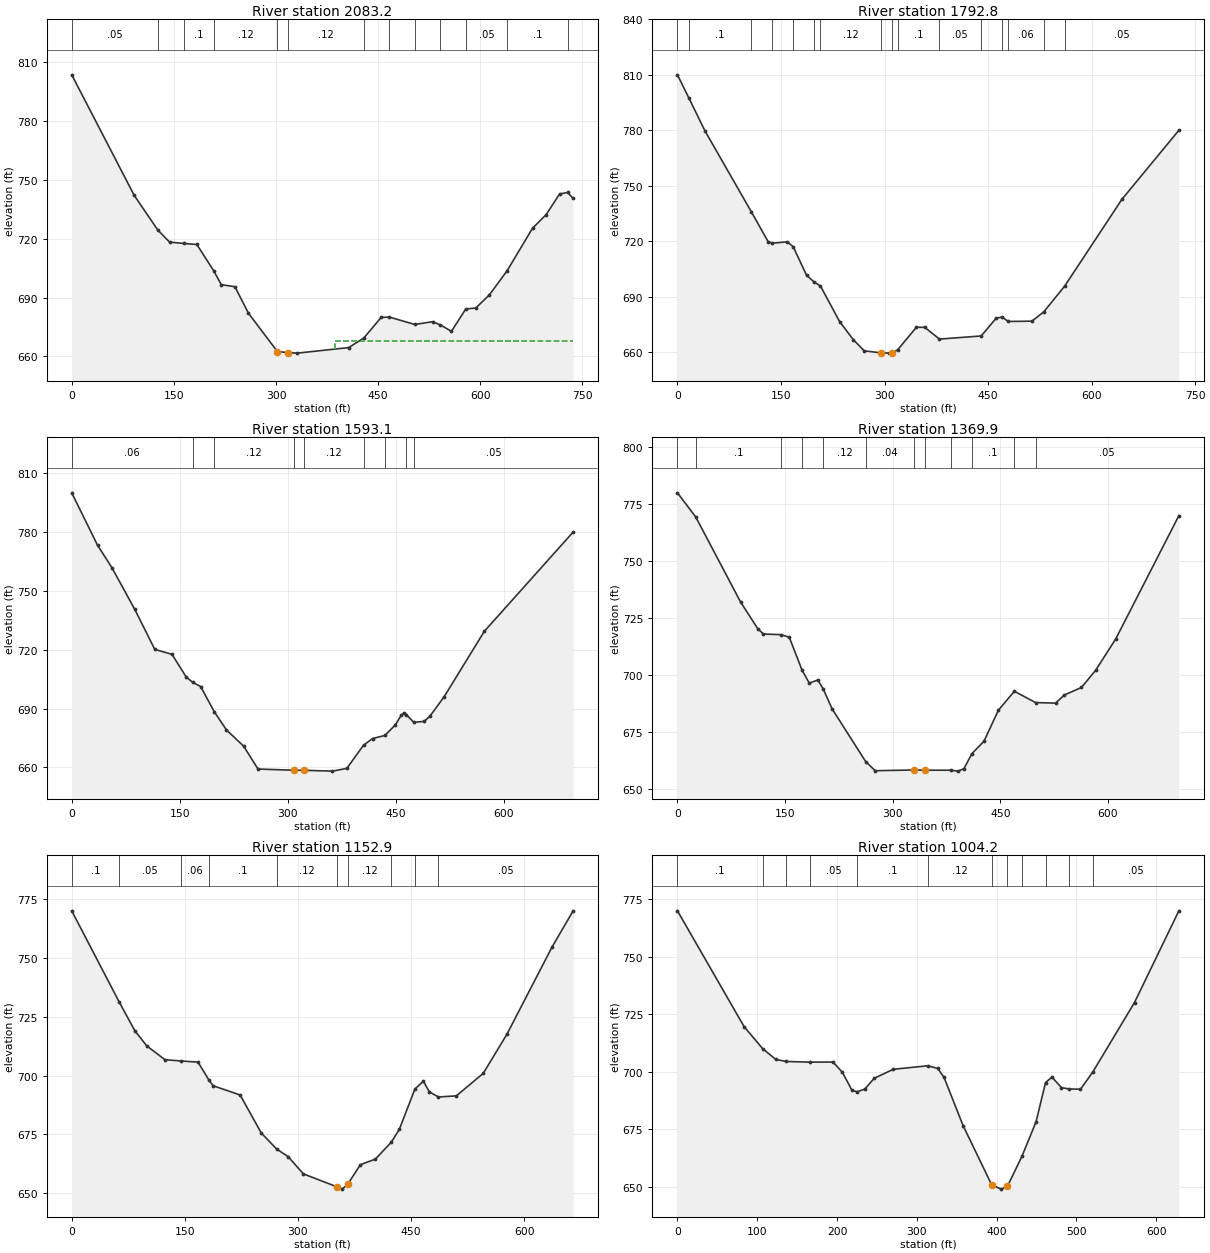
Type RM Length L Ch R = 1 ,2083.2  ,270.7,290.5,307.7
XS GIS Cut Line= 3
     1764263.482      441150.323     1764022.026      441347.001
     1763686.471       441607.61
#Sta/Elev= 30
       0  803.67    91.8  742.11  126.49724.4298   143.7   718.3  164.59717.6078
   183.7  717.08  208.87703.4509   219.6  696.58   239.6  695.54   259.5  682.02
     302  662.44     317  661.93   331.3  661.64   406.7  664.47  429.05669.4075
   454.4  679.86  466.45680.0312  503.85676.2645   529.8  677.68  541.25 676.065
   557.6  672.77  578.64684.1757   593.3  684.66   613.2  691.33  639.19703.6066
   676.7  725.39   696.6   732.3   716.4  742.85  728.23 743.634   736.3  740.62
#Mann= 13 ,-1 , 0
       0     .05       0  126.49     .06       0  164.59      .1       0
  208.87     .12       0     302    .045       0     317     .12       0
  429.05      .1       0  466.45    .016       0  503.85     .05       0
  541.25      .1       0  578.64     .05       0  639.19      .1       0
  728.23     .05       0
#XS Ineff= 2 , 0
                          387.11           667.8
Permanent Ineff=
       F       F
Bank Sta=302,317
XS Rating Curve= 0 ,0
Exp/Cntr=0.3,0.1

Type RM Length L Ch R = 1 ,1792.8  ,195.6,199.7,204.9
XS GIS Cut Line= 3
     1764181.491        441030.5     1763625.791      441154.101
     1763471.434      441124.444
#Sta/Elev= 30
       0     810   16.48797.5074    39.8   779.7  107.25735.7762   131.4  719.73
  137.51718.9288   159.2  719.65  167.76716.9672   187.1  701.54  198.02697.9353
  207.18695.7726   234.9  676.54   254.8  666.72   270.7  660.66   294.6  659.64
   306.5  659.45   310.5  659.48  319.05661.2704   346.3  673.47   358.3   673.4
  379.57667.0428  440.08668.7366   461.8  678.36  470.34 678.967  479.24676.5734
   513.6  676.74  530.85681.7981  561.11695.7484   643.9  742.61   726.5     780
#Mann= 16 ,-1 , 0
       0     .06       0   16.48      .1       0  107.25     .05       0
  137.51     .06       0  167.76      .1       0  198.02      .1       0
  207.18     .12       0   294.6    .045       0   310.5     .12       0
  319.05      .1       0  379.57     .05       0  440.08    .016       0
  470.34     .05       0  479.24     .06       0  530.85     .06       0
  561.11     .05       0
Bank Sta=294.6,310.5
XS Rating Curve= 0 ,0
Exp/Cntr=0.3,0.1

Type RM Length L Ch R = 1 ,1593.1  ,222.3,223.2,219.9
XS GIS Cut Line= 2
     1764155.823      440886.801     1763461.791      440946.895
#Sta/Elev= 30
       0     800    35.8  773.32    55.7   761.9    87.6  740.55   115.4  720.16
   139.3  717.66   159.2     706  168.26 703.361   179.1  701.23   197.9688.4669
     215   679.1   238.8  670.86   258.8  659.17   308.3  658.58   323.3  658.53
   362.2  658.11   382.2  659.52  405.43671.3306     418  674.74  435.07676.2944
   449.8  681.76   457.8  686.67   461.8  687.79  464.72 686.914   475.3 682.968
   489.6  683.49   497.6  686.12   517.5  696.09   573.2  729.39   696.6     780
#Mann= 9 ,-1 , 0
       0     .06       0  168.26      .1       0   197.9     .12       0
   308.3    .045       0   323.3     .12       0  405.43      .1       0
  435.07    .016       0  464.72      .1       0   475.3     .05       0
Bank Sta=308.3,323.3
XS Rating Curve= 0 ,0
Exp/Cntr=0.3,0.1

Type RM Length L Ch R = 1 ,1369.9  ,218.4,217,207.2
XS GIS Cut Line= 2
     1764161.391      440695.201     1763464.003      440740.589
#Sta/Elev= 30
       0  780.01   25.57769.3697    87.9  732.18   111.8   720.5   119.8  718.09
  143.96717.8312   155.8  716.71  173.56702.3562   183.7  696.56   195.7  697.96
  203.16693.9974   215.6  685.26  262.36662.1676   275.6  658.16   329.4  658.48
   344.4  658.39  380.75658.3795   391.4  657.98   399.4  659.09  410.35665.6226
   427.3  671.12   447.3  684.67  469.54693.0084  499.14688.0422   527.1   687.8
   539.1  691.31   563.1  694.67     583  702.23     611  716.01   698.9     770
#Mann= 12 ,-1 , 0
       0     .05       0   25.57      .1       0  143.96     .06       0
  173.56      .1       0  203.16     .12       0  262.36     .04       0
   329.4    .045       0   344.4     .04       0  380.75     .12       0
  410.35      .1       0  469.54    .016       0  499.14     .05       0
Bank Sta=329.4,344.4
XS Rating Curve= 0 ,0
Exp/Cntr=0.3,0.1

Type RM Length L Ch R = 1 ,1152.9  ,144.2,148.7,159.9
XS GIS Cut Line= 3
      1764109.18      440462.801     1763754.308      440517.207
     1763464.583      440616.009
#Sta/Elev= 30
       0     770   62.64731.4309    83.8  718.99    99.7  712.54   123.7  706.72
  144.96706.1814   167.5   705.7  182.16697.9775   187.5  695.67   223.4  691.71
   251.3  675.62   271.8668.7531   287.2  665.48   307.2   658.2   351.5  652.72
     359  651.71   366.5     654   382.9   662.1   402.8  664.47  423.96671.6862
   434.6  677.17  455.17694.2235   466.4  697.62   474.3  693.07  486.37690.8913
   510.1  691.34   545.9  700.92   577.7   717.8   637.3  754.72   665.1     770
#Mann= 10 ,-1 , 0
       0      .1       0   62.64     .05       0  144.96     .06       0
  182.16      .1       0   271.8     .12       0   351.5    .045       0
   366.5     .12       0  423.96      .1       0  455.17    .016       0
  486.37     .05       0
Bank Sta=351.5,366.5
XS Rating Curve= 0 ,0
Exp/Cntr=0.3,0.1

Type RM Length L Ch R = 1 ,1004.2  ,197.2,200.2,203.6
XS GIS Cut Line= 2
     1764095.075      440381.517     1763466.657      440385.935
#Sta/Elev= 30
       0     770    83.5  719.68  106.88710.0628   123.3  705.41  136.42 704.543
  165.95704.2473   194.9   704.3   206.8  699.79   218.8  691.95  225.03691.3826
   234.7  692.52   246.6  697.24   270.5  701.15  313.64 702.664   326.2   701.5
   334.1  697.62     358  676.65   393.8  650.95   405.7  649.07   413.6  650.29
  431.78663.3767   449.4  678.31  461.32 695.387   469.3  697.75   481.3  693.16
  490.85 692.601   505.1  692.47  520.39699.8853   572.8  730.16   628.4     770
#Mann= 12 ,-1 , 0
       0      .1       0  106.88     .05       0  136.42     .06       0
  165.95     .05       0  225.03      .1       0  313.64     .12       0
   393.8    .045       0   413.6     .12       0  431.78      .1       0
  461.32      .1       0  490.85    .016       0  520.39     .05       0
Bank Sta=393.8,413.6
XS Rating Curve= 0 ,0
Exp/Cntr=0.3,0.1

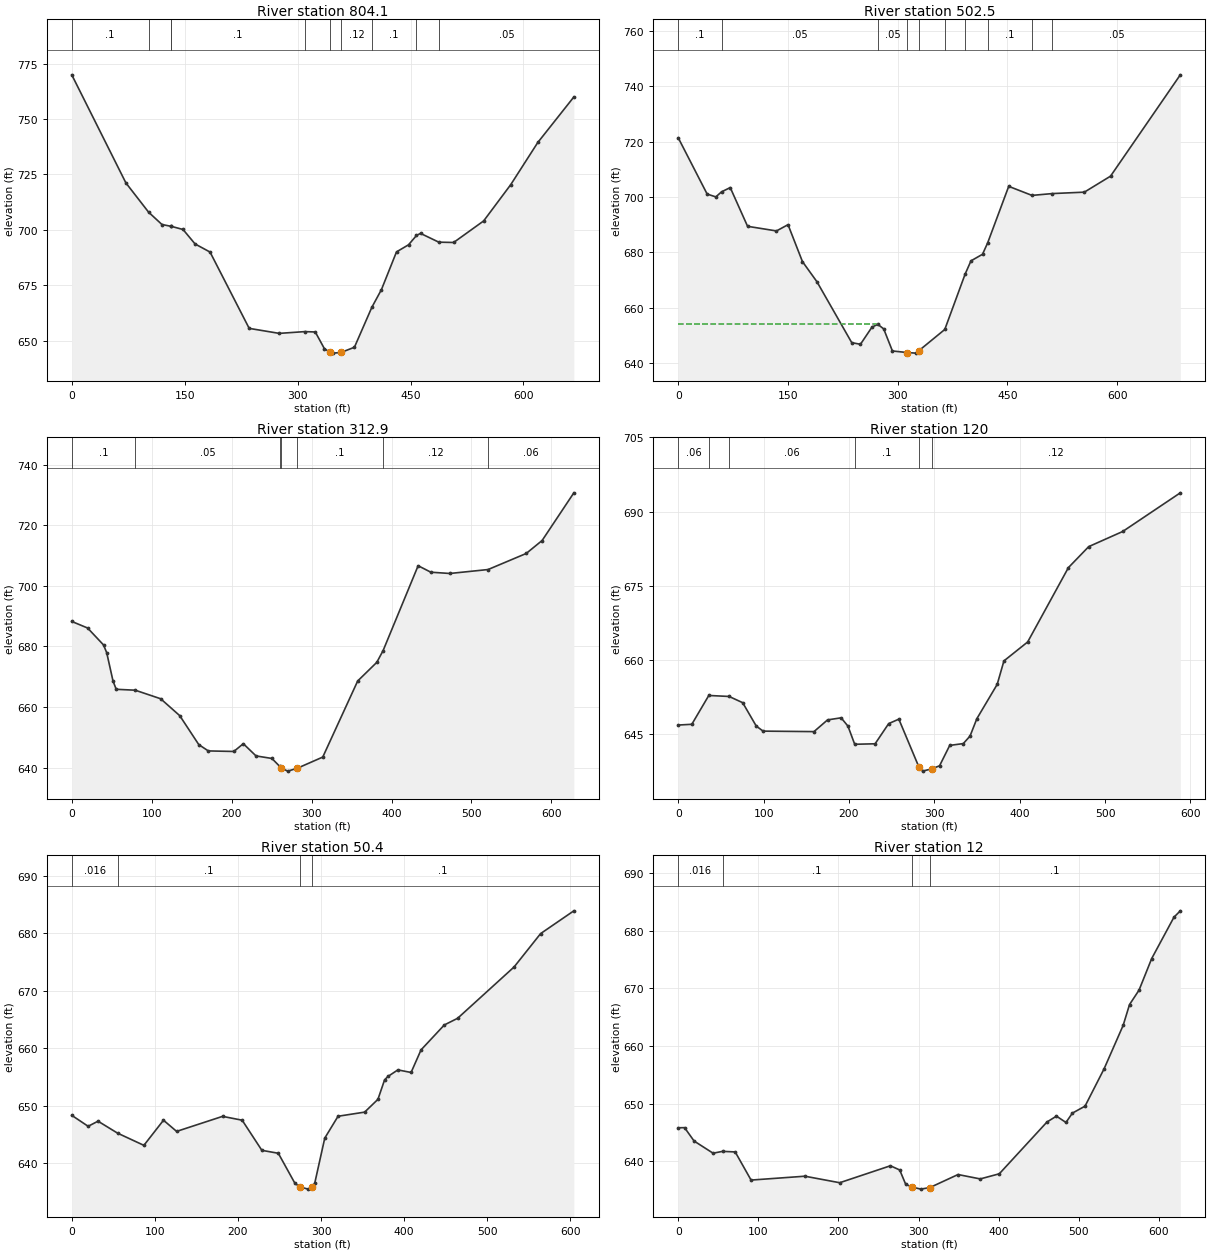
Type RM Length L Ch R = 1 ,804.1   ,304.4,301.6,298.6
XS GIS Cut Line= 2
     1764089.864      440230.874     1763425.541      440170.801
#Sta/Elev= 30
       0     770    71.9  721.19  102.08 707.961   119.8   702.4  131.74701.5935
  132.44701.5484   147.8  700.15   163.8  693.62   183.7  689.95   235.7  655.49
   275.6  653.23  309.67654.0276   323.5  653.86   335.5  646.39   342.6  644.75
   347.5  644.31   357.6   644.6   375.5  646.96  398.64665.0021   411.4     673
   431.4  690.03   447.4  693.24  457.96697.4483   463.3  698.39  487.61694.4229
   507.3  694.28   547.2  704.02   583.2  720.42   619.1  739.44     667     760
#Mann= 10 ,-1 , 0
       0      .1       0  102.08     .05       0  131.74     .06       0
  132.44      .1       0  309.67     .12       0   342.6    .045       0
   357.6     .12       0  398.64      .1       0  457.96    .016       0
  487.61     .05       0
Bank Sta=342.6,357.6
XS Rating Curve= 0 ,0
Exp/Cntr=0.3,0.1

Type RM Length L Ch R = 1 ,502.5   ,188.4,189.6,190.6
XS GIS Cut Line= 3
     1764071.608      439977.101     1763875.894      439902.801
     1763398.888      439898.523
#Sta/Elev= 30
       0  721.35    39.5  701.07    51.4  700.04    59.2  701.87    71.1   703.4
    94.8  689.43   134.3  687.76   150.1  690.02   169.8  676.71   189.6  669.45
   237.2  647.47   249.1  646.88     265  653.12     273  654.04   280.9  652.43
   292.8  644.47   312.7  643.91   324.6  643.69   328.6  644.49   364.4  652.22
   392.2  672.18   400.2  676.97     416  679.35   423.1683.5098   451.8  703.85
   483.6  700.58   511.5  701.24   555.2  701.75     591  707.52   686.4  744.07
#Mann= 10 ,-1 , 0
       0      .1       0    59.2     .05       0     273     .05       0
   312.7    .045       0   328.6     .12       0   364.4     .06       0
   392.2    .016       0   423.1      .1       0   483.6     .06       0
   511.5     .05       0
#XS Ineff= 2 , 0
       0     273   654.2               0
Permanent Ineff=
       F       F
Bank Sta=312.7,328.6
XS Rating Curve= 0 ,0
Exp/Cntr=0.3,0.1

Type RM Length L Ch R = 1 ,312.9   ,183.2,192.8,201.1
XS GIS Cut Line= 3
     1764019.525      439760.088     1763941.834      439720.157
     1763401.469      439699.324
#Sta/Elev= 30
       0  688.23    19.8  686.06    39.7  680.48    43.7  677.92    51.6  668.56
    55.6  665.83    79.4  665.53   111.2  662.71   135.1  657.12   158.9  647.57
   170.8  645.49   202.7  645.31   214.6  647.87   230.5  643.84   250.4     643
   259.9  640.45   262.3  639.77   270.3  638.82   282.2  639.78     314  643.46
   357.7  668.58   381.6  674.73   389.5  678.62   433.3  706.62   449.2  704.48
     473  704.06   520.8  705.36   568.5  710.66   588.4  714.94   628.1  730.68
#Mann= 7 ,-1 , 0
       0      .1       0    79.4     .05       0   259.9    .045       0
   262.3    .045       0   282.2      .1       0   389.5     .12       0
   520.8     .06       0
Bank Sta=262.3,282.2
XS Rating Curve= 0 ,0
Exp/Cntr=0.3,0.1

Type RM Length L Ch R = 1 ,120     ,70.8,69.6,69.8
XS GIS Cut Line= 3
     1763997.823        439642.9      1763764.75      439531.355
     1763444.438       439453.23
#Sta/Elev= 30
       0  646.84    15.9  646.99    35.8  652.82    59.6  652.62    75.5  651.36
    91.4  646.63    99.4  645.61     159  645.51   174.9  647.88   190.8   648.3
   198.8  646.62   206.7  642.95   230.6  643.05   246.5  647.13   258.4  648.03
     282  638.31   286.2  637.52     297  637.98   306.1   638.6     318  642.72
   333.9  643.09   341.8  644.61   349.8  648.13   373.6  655.06   381.5  659.81
   409.3  663.64     457  678.67   480.8  682.92   520.6  685.98   588.1   693.8
#Mann= 6 ,-1 , 0
       0     .06       0    35.8    .016       0    59.6     .06       0
   206.7      .1       0     282    .045       0     297     .12       0
Bank Sta=282,297
XS Rating Curve= 0 ,0
Exp/Cntr=0.3,0.1

Type RM Length L Ch R = 1 ,50.4    ,33.2,38.4,38.9
XS GIS Cut Line= 3
     1763988.709      439574.324     1763769.959      439464.949
     1763422.302      439372.501
#Sta/Elev= 30
       0  648.31    19.7   646.4    31.6  647.29    55.2   645.2    86.8  643.08
   110.4  647.46   126.2  645.51   181.5  648.13   205.1  647.46   228.8  642.21
   248.6   641.7   268.6  636.46   274.5  635.84   284.5  635.45   289.5  635.81
   292.5  636.52   304.5  644.34   320.5  648.15   352.5  648.87   368.5   651.1
   376.5  654.49   380.5  655.08   392.5  656.23   408.4  655.78   420.4  659.72
   448.4  664.06   464.4  665.22   532.4  674.17   564.3  679.98   604.3  683.95
#Mann= 4 ,-1 , 0
       0    .016       0    55.2      .1       0   274.5    .045       0
   289.5      .1       0
#XS Ineff= 2 , 0
       0  241.36                       0
Permanent Ineff=
       F       F
Bank Sta=274.5,289.5
XS Rating Curve= 0 ,0
Exp/Cntr=0.3,0.1

Type RM Length L Ch R = 1 ,12      ,24,12,4.4
XS GIS Cut Line= 4
     1763999.425      439553.813     1763759.224      439424.758
     1763712.967      439409.282     1763413.487      439350.688
#Sta/Elev= 30
       0  645.83     7.9  645.85    19.8  643.53    43.5  641.42    55.3  641.74
    71.1  641.64    90.9  636.76   158.1  637.43   201.5   636.3   264.8  639.24
   276.4  638.51   283.9  636.02   291.4  635.57   302.7  635.19     314  635.46
   349.2  637.72   376.9  636.96   400.7  637.85   460.2  646.83     472  647.85
   483.9  646.75   491.9  648.37   507.7  649.58   531.5  656.06   555.3   663.6
   563.2  667.19   575.1   669.7   590.9  675.18   618.7  682.35   626.6  683.45
#Mann= 4 ,-1 , 0
       0    .016       0    55.3      .1       0   291.4    .045       0
     314      .1       0
#XS Ineff= 2 , 0
       0   268.7           349.2       0
Permanent Ineff=
       F       F
Bank Sta=291.4,314
XS Rating Curve= 0 ,0
Exp/Cntr=0.3,0.1

Chan Stop Cuts=-1
Use User Specified Reach Order=0
Composite Channel Slope=5